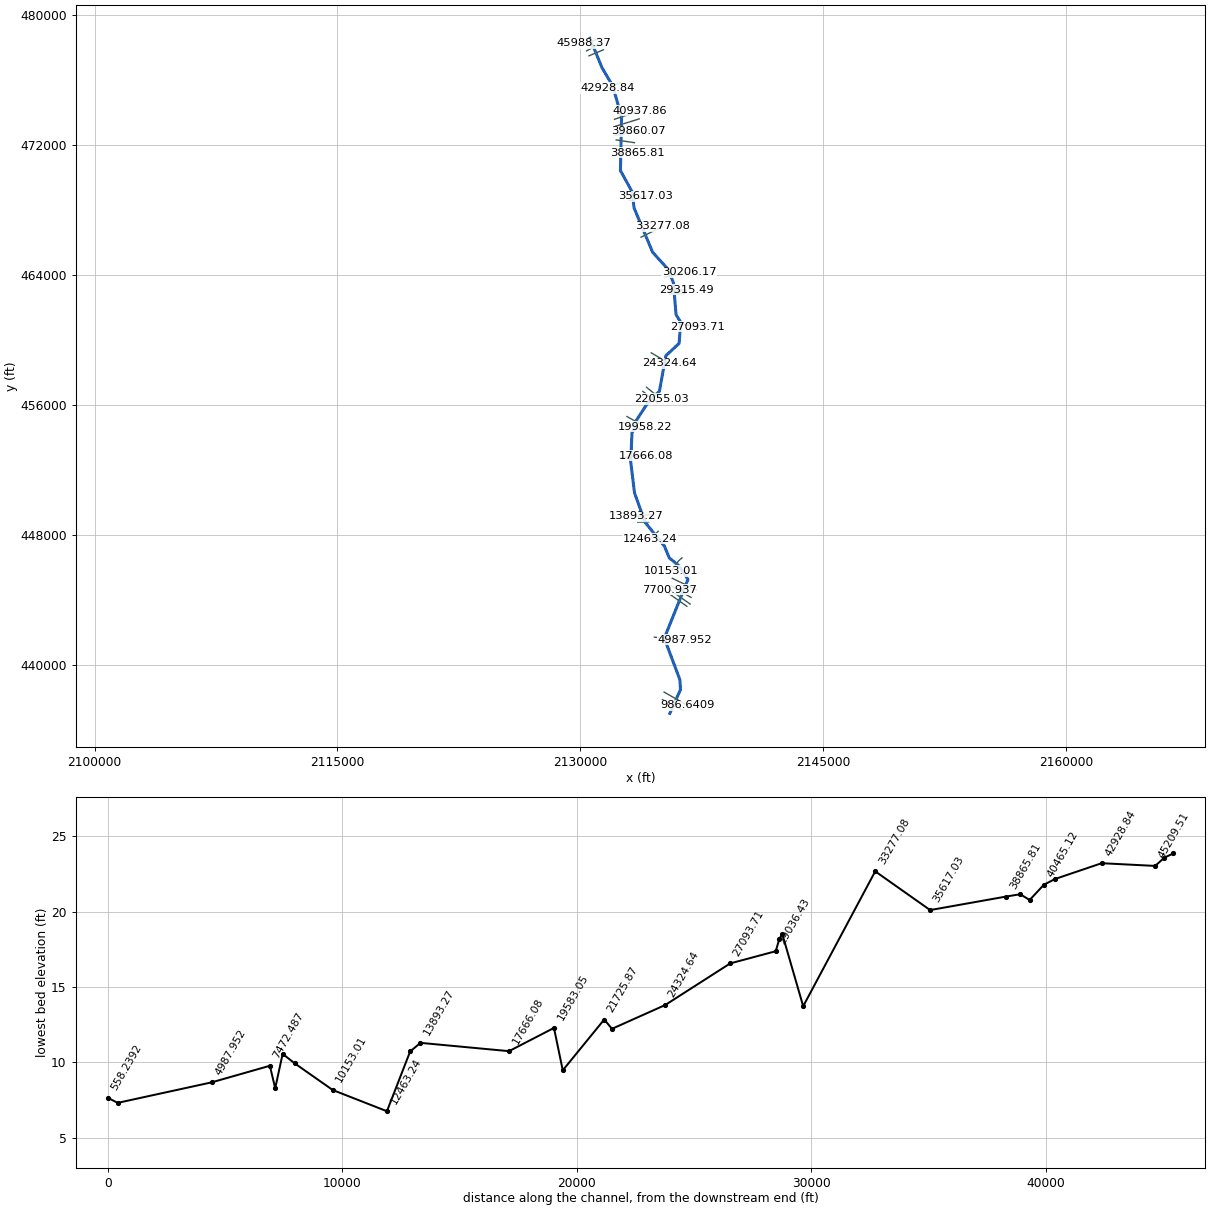
--- WacissaModel.prj (project) ---

Proj Title=WacissaModel
Current Plan=p01
Default Exp/Contr=0.3,0.1
English Units
Geom File=g01
Flow File=f01
Plan File=p01
Y Axis Title=Elevation
X Axis Title(PF)=Main Channel Distance
X Axis Title(XS)=Station
BEGIN DESCRIPTION:
END DESCRIPTION:
DSS Export Rating Curves= 0
DSS Export Rating Curve Sorted= 0
DSS Export Volume Flow Curves= 0
DXF Filename=..\..\06 Data-QAQC\From District\Wacissa HEC-RAS model\WacissaSEFA.
DXF OffsetX= 0
DXF OffsetY= 0
DXF ScaleX= 1
DXF ScaleY= 10

--- WacissaModel.p01 (plan) ---

Plan Title=Plan 01
Program Version=4.10
Short Identifier=Plan 01
Geom File=g01
Flow File=f01
Subcritical Flow
K Sum by GR= 0
Std Step Tol= 0.01
Critical Tol= 0.01
Num of Std Step Trials= 20
Max Error Tol= 0.3
Flow Tol Ratio= 0.001
Split Flow NTrial= 30
Split Flow Tol= 0.02
Split Flow Ratio= 0.02
Log Output Level= 0
Friction Slope Method= 1
Unsteady Friction Slope Method= 2
Unsteady Bridges Friction Slope Method= 1
Parabolic Critical Depth
Global Vel Dist= 10 , 25 , 10
Global Log Level= 0
CheckData=True
Encroach Param=-1 ,0,0, 0
Computation Interval=1HOUR
Output Interval=1HOUR
Run HTab= 0
Run UNet= 0
Run PostProcess= 0
Run WQNet= 0
UNET Theta= 1
UNET Theta Warmup= 1
UNET ZTol= 0.02
UNET ZSATol= 0.05
UNET MxIter= 20
UNET MaxInSteps= 0
UNET DtIC= 0
UNET DtMin= 0
UNET MaxCRTS= 20
UNET WFStab= 2
UNET SFStab= 1
UNET WFX= 1
UNET SFX= 1
UNET DSS MLevel= 4
UNET DZMax Abort= 100
UNET Convert EG Bridges= 0
UNET Use Existing IB Tables=-1
UNET Froude Reduction=False
UNET Froude Limit= 1
UNET Froude Power= 10
UNET Time Slicing=0,0, 5
UNET Junction Losses=0
Instantaneous Interval=1HOUR
Write IC File= 0
Write IC File at Sim End=0
Echo Input=False
Echo Parameters=False
Echo Output=False
Write Detailed= 0
WQ AD Non Conservative
WQ ULTIMATE=-1
WQ Max Comp Step=1HOUR
WQ Output Interval=15MIN
WQ Output Selected Increments= 0
WQ Output face flow=0
WQ Output face velocity=0
WQ Output face area=0
WQ Output face dispersion=0
WQ Output cell volume=0
WQ Output cell surface area=0
WQ Output cell continuity=0
WQ Output cumulative cell continuity=0
WQ Output face conc=0
WQ Output face dconc_dx=0
WQ Output face courant=0
WQ Output face peclet=0
WQ Output face adv mass=0
WQ Output face disp mass=0
WQ Output cell mass=0
WQ Output cell source sink temp=0
WQ Output cell source sink nsm=0
WQ Output MaxMinRange=-1
WQ Daily Max Min Mean=-1
WQ Daily Range=0
WQ Daily Time=0
WQ Create Restart=0
WQ Fixed Restart=0
WQ System Summary=0
WQ Use Fixed Temperature=0
Sorting and Armoring Iterations= 10
XS Update Threshold= 0.02
Hydraulics Update Threshold= 0.02
Energy Slope Method= 1
Volume Change Method= 0
XS Weighting Method= 0
Number of US Weighted Cross Sections= 1
Number of DS Weighted Cross Sections= 1
Upstream XS Weight=0.25
Main XS Weight=0.5
Downstream XS Weight=0.25
Number of DS XS's Weighted with US Boundary= 1
Upstream Boundary Weight= 1
Weight of XSs Associated with US Boundary= 0
Number of US XS's Weighted with DS Boundary= 1
Downstream Boundary Weight= 0.5
Weight of XSs Associated with DS Boundary= 0.5
Sediment Output Level= 4
Mass or Volume Output= 0
Output Increment Type= 1
Profile and TS Output Increment= 10
XS Output Flag= 0
XS Output Increment= 10
Disregard all LS=0
Disregard all Conn=0
Disregard all Breaches=0
Disregard all Pumps=0

--- WacissaModel.f01 (steady flow) ---

Flow Title=WacissaSEFA
Program Version=4.10
Number of Profiles= 6
Profile Names=PF 1,PF 2,PF 3,PF 4,PF 5,PF 6
River Rch & RM=Wacissa,SEFA            ,45988.37
     233     254     357     518     563     670
Boundary for River Rch & Prof#=Wacissa,SEFA            , 1
Up Type= 0
Dn Type= 1
Dn Known WS=11.24
Boundary for River Rch & Prof#=Wacissa,SEFA            , 2
Up Type= 0
Dn Type= 1
Dn Known WS=11.29
Boundary for River Rch & Prof#=Wacissa,SEFA            , 3
Up Type= 0
Dn Type= 1
Dn Known WS=11.66
Boundary for River Rch & Prof#=Wacissa,SEFA            , 4
Up Type= 0
Dn Type= 1
Dn Known WS=12.22
Boundary for River Rch & Prof#=Wacissa,SEFA            , 5
Up Type= 0
Dn Type= 1
Dn Known WS=12.46
Boundary for River Rch & Prof#=Wacissa,SEFA            , 6
Up Type= 0
Dn Type= 1
Dn Known WS=13
Observed WS=Wacissa         ,SEFA            ,40937.86,,26.41,26.52,26.92,27.63,27.7,27.94
Observed WS=Wacissa         ,SEFA            ,29315.49,,21.27,21.3,21.59,22.23,22.48,23.02
Observed WS=Wacissa         ,SEFA            ,29036.43,,20.76,20.82,21.16,21.74,21.91,22.36
DSS Import GetInterval= 0
DSS Import GetPeak= 0
DSS Import FillOption= 0

--- WacissaModel.g01 (geometry) ---

Geom Title=WacissaSEFA
Program Version=4.10

River Reach=Wacissa         ,SEFA
Reach XY= 30
2130596.80979702478579.9648191632131349.41393483476759.652186841
2132004.36898977475658.5950057512132552.48600376473737.122142673
2132482.22630176470441.9440217472133201.84461316469139.860667914
2133326.84436318468139.8606994152134469.20559549465421.110559508
2135424.06654668 464369.027361842135756.30997667463531.809876174
 2135917.1223191461577.3607010842136205.31662458461112.082760245
2136106.35848919459811.7356234192135286.91393384459047.846731246
  2134887.608302456853.4023012522134308.18131125456362.082745835
2133427.10794216455014.4496143312133426.70013458454658.655050337
2133196.63629025454329.9647628372133116.34084716452537.429962084
2133350.71603459450614.6870884152134004.37614459448802.224834085
2135198.80617043447336.0410866742135499.15333876446613.818777829
2136091.16724658446132.9161963312136653.66743392445289.166243419
 2135191.0230495441668.2958604992136154.88267034439114.860678673
2136191.34093076438505.485585079 2135532.4869335437045.415998667

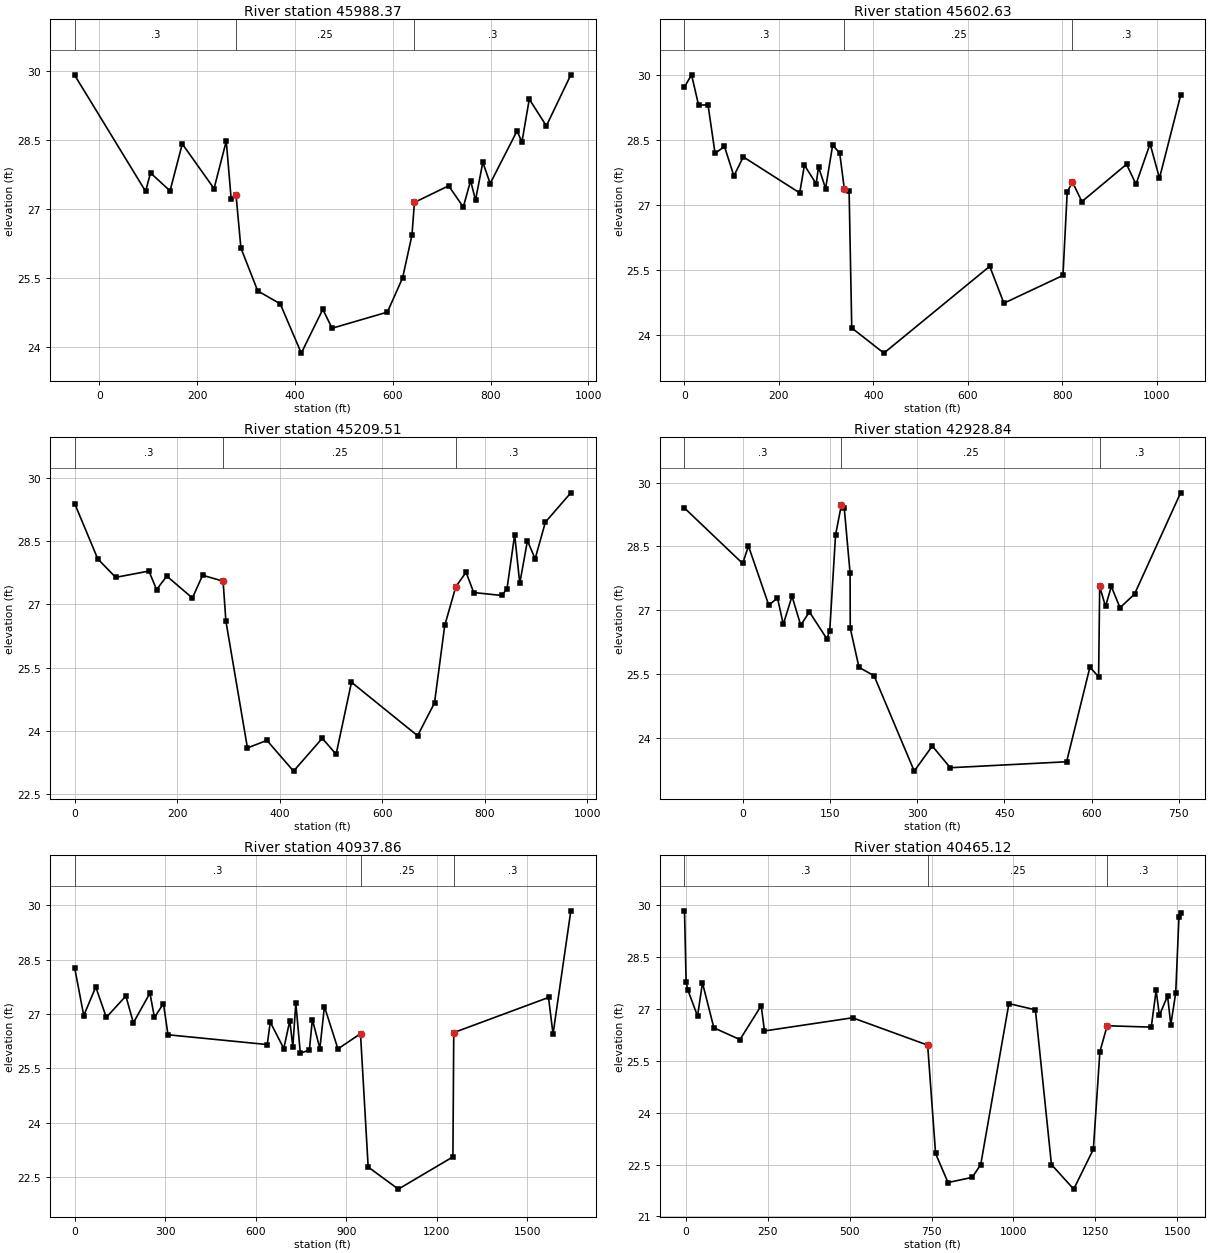
Type RM Length L Ch R = 1 ,45988.37,317.84,385.74,478.06
XS GIS Cut Line= 4
2131190.63811983 478563.658339332131142.88678885478548.832335502
2130270.08505675 478277.841735752130222.33372577478263.015731922
#Sta/Elev= 30
     -50 29.8982   94.89   27.38  104.87   27.78  144.83   27.39   169.8   28.41
  234.72   27.44  259.69   28.47  269.68   27.22  279.66    27.3  289.65   26.15
     324   25.22     370   24.94     413   23.87     457   24.82     476   24.41
     589   24.76     620    25.5  639.23   26.43  644.23   27.14  714.14    27.5
  744.11   27.04  759.09   27.61  769.08   27.19  784.06   28.01  799.04   27.55
  853.98   28.69  863.96   28.45  878.95   29.38   913.9    28.8   963.9 29.9081
#Mann= 3 , 0 , 0
     -50      .3       0  279.66     .25       0  644.23      .3       0
Bank Sta=279.66,644.23
XS Rating Curve= 0 ,0
Exp/Cntr=0.3,0.1

Type RM Length L Ch R = 1 ,45602.63,435.3,393.12,343.55
XS GIS Cut Line= 3
2131316.88578469478311.7632558352130415.92925325477822.571977004
2130394.13466559477810.738196089
#Sta/Elev= 30
       0   29.72   14.93      30   29.86    29.3   49.77   29.31    64.7   28.19
    84.6   28.35  104.51   27.67  124.42   28.11  243.86   27.28  253.81   27.92
  278.69   27.49  283.67   27.88   298.6   27.38  313.53   28.38  328.46    28.2
  338.42   27.36  348.37   27.33     354   24.17     422   23.59     646   25.59
     676   24.74     801   25.38     810    27.3  821.15   27.53  841.06   27.08
  935.62   27.94  955.52   27.48  985.38   28.41 1005.29   27.62    1050 29.5266
#Mann= 3 , 0 , 0
       0      .3       0  338.42     .25       0  821.15      .3       0
Bank Sta=338.42,821.15
XS Rating Curve= 0 ,0
Exp/Cntr=0.3,0.1

Type RM Length L Ch R = 1 ,45209.51,2265.64,2280.67,2298.55
XS GIS Cut Line= 3
2131433.02498809477875.3622257562130584.85870543477523.425921753
2130538.93521094 477504.37052513
#Sta/Elev= 30
       0   29.39   44.92   28.08   79.85   27.64  144.73   27.79   159.7   27.35
  179.66   27.67  229.57   27.15  249.53   27.69  289.46   27.55     295    26.6
     337   23.59     375   23.77     427   23.04     483   23.82     510   23.44
     540   25.15     669   23.88     702   24.66     722    26.5  743.61   27.42
  763.57   27.76  778.55   27.28  833.44   27.21  843.42   27.37   858.4   28.65
  868.38    27.5  883.35   28.51  898.32   28.08  918.28   28.95     968 29.6473
#Mann= 3 , 0 , 0
       0      .3       0  289.46     .25       0  743.61      .3       0
Bank Sta=289.46,743.61
XS Rating Curve= 0 ,0
Exp/Cntr=0.3,0.1

Type RM Length L Ch R = 1 ,42928.84,2011.8,1990.98,1984.42
XS GIS Cut Line= 4
 2132461.3483616475851.7991404182132369.17534676475813.015956745
2131725.13201544475542.0250289142131675.10970229 475520.97738756
#Sta/Elev= 30
    -100 29.4024       0    28.1    9.98   28.51   44.92   27.12   59.89   27.29
   69.87   26.67   84.85   27.33   99.82   26.65  114.79   26.96  144.74   26.33
  149.73   26.52  159.71   28.77  169.69   29.47  174.68    29.4  184.67   27.88
     185   26.58     200   25.66     226   25.46     295   23.22     326   23.81
     357    23.3     557   23.44     597   25.66     612   25.44  613.89   27.56
  623.87   27.09  633.85   27.56  648.82   27.06  673.78   27.38     753 29.7601
#Mann= 3 , 0 , 0
    -100      .3       0  169.69     .25       0  613.89      .3       0
Bank Sta=169.69,613.89
XS Rating Curve= 0 ,0
Exp/Cntr=0.3,0.1

Type RM Length L Ch R = 1 ,40937.86,449.3,472.74,433.5
BEGIN DESCRIPTION:
USGS Gage
END DESCRIPTION:
XS GIS Cut Line= 3
2132115.78116852 473599.337313252133629.10688201474106.125341669
2133675.63703437474121.707528615
#Sta/Elev= 30
       0   28.27   29.92   26.96   69.82   27.75  104.73   26.91  169.57    27.5
   194.5   26.76  249.36   27.58  264.33   26.91  294.25   27.29  309.21   26.43
  638.37   26.16  648.35   26.78  693.23   26.05  713.18   26.82  723.16    26.1
  733.13    27.3  748.09   25.92  778.02   26.01  787.99   26.85  812.93   26.05
  827.89   27.21  872.77   26.04  947.58   26.46     973   22.78    1073   22.17
    1254   23.06 1256.79   26.49 1570.99   27.46 1585.95   26.45    1645 29.8508
#Mann= 3 , 0 , 0
       0      .3       0  947.58     .25       0 1256.79      .3       0
Bank Sta=947.58,1256.79
XS Rating Curve= 0 ,0
Exp/Cntr=0.3,0.1

Type RM Length L Ch R = 1 ,40465.12,683.15,605.05,573.86
XS GIS Cut Line= 3
2132195.46977872473175.5342514312132200.24589458473177.013682827
2133643.18428168473623.972762674
#Sta/Elev= 30
      -5 29.8302       0   27.76    4.99   27.55    34.9   26.79   49.85   27.75
   84.75   26.45  164.52   26.11  229.33   27.09   239.3   26.36  508.51   26.74
  737.84   25.95     762   22.82     800   21.98     874   22.13     900    22.5
     986   27.15    1067   26.97    1116    22.5    1184   21.79    1244   22.94
    1264   25.76 1286.24   26.51 1420.84   26.47  1435.8   27.53 1445.77   26.81
  1470.7   27.37 1480.67   26.54 1495.62   27.46 1505.59   29.66 1510.58   29.77
#Mann= 3 , 0 , 0
      -5      .3       0  737.84     .25       0 1286.24      .3       0
Bank Sta=737.84,1286.24
XS Rating Curve= 0 ,0
Exp/Cntr=0.3,0.1

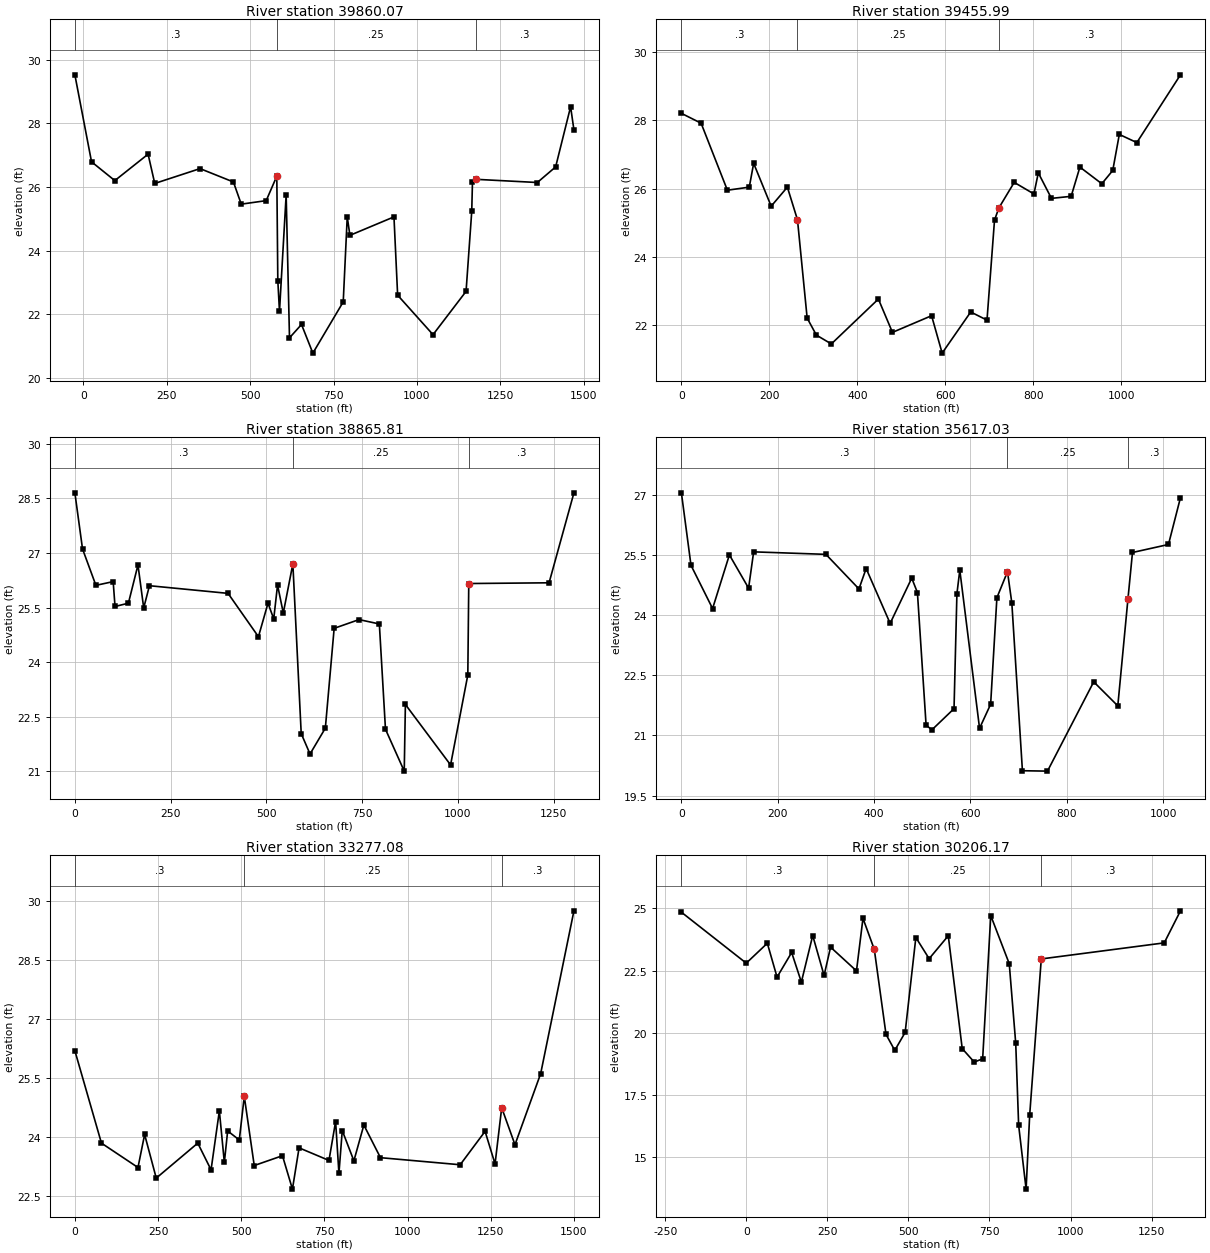
Type RM Length L Ch R = 1 ,39860.07,606.15,404.08,329.22
XS GIS Cut Line= 3
2132143.91514025472606.2669921452132168.57174534472610.396377757
2133618.54883227472853.232506245
#Sta/Elev= 30
     -25 29.5224   24.92   26.79   94.69    26.2  194.36   27.03   214.3   26.11
     350 26.5764     450 26.1562  473.44   25.46   548.2   25.57     580   26.34
     583   23.06     588   22.09     608   25.75     618   21.26     654   21.68
     688   20.78     779   22.39     791   25.06     799   24.48     931   25.06
     942    22.6    1048   21.36    1147   22.72    1164   25.23 1166.17   26.15
 1176.13   26.24 1360.53   26.14 1415.35   26.63  1460.2   28.52 1470.17   27.79
#Mann= 3 , 0 , 0
     -25      .3       0     580     .25       0 1176.13      .3       0
Bank Sta=580,1176.13
XS Rating Curve= 0 ,0
Exp/Cntr=0.3,0.1

Type RM Length L Ch R = 1 ,39455.99,585.21,590.18,583.98
XS GIS Cut Line= 3
2132221.36199409472328.8474001742133245.49642876472173.995675758
2133343.60129008472159.161971866
#Sta/Elev= 30
       0   28.21   44.82   27.92  104.57   25.95  154.37   26.04  164.33   26.74
  204.17   25.48     241   26.04     264   25.08     286   22.19     307   21.69
     341   21.43     448   22.75     480   21.77     569   22.26     593   21.16
     658   22.37     695   22.13   712.1   25.07  722.05   25.43  756.91   26.18
  801.73   25.84  811.69   26.46  841.57   25.71  886.38   25.77   906.3   26.63
   956.1   26.14     981   26.53  995.94   27.59 1035.78   27.35    1135 29.3422
#Mann= 3 , 0 , 0
       0      .3       0     264     .25       0  722.05      .3       0
Bank Sta=264,722.05
XS Rating Curve= 0 ,0
Exp/Cntr=0.3,0.1

Type RM Length L Ch R = 1 ,38865.81,2900.33,3248.77,3380.07
XS GIS Cut Line= 2
2132231.92004383471737.5946456642133520.00670651471540.510394171
#Sta/Elev= 30
       0   28.65   19.97   27.11   54.92   26.11     100 26.2127  104.85   25.53
  139.79   25.62  164.76   26.67  179.73   25.49  194.71    26.1     400 25.8898
  479.29    24.7  504.26   25.62  519.23   25.19  529.22   26.12   544.2   25.35
  569.16    26.7     591   22.04     614   21.48     654   22.19     677   24.93
     742   25.17     795   25.05     811   22.16     860   21.01     863   22.84
     981   21.18    1026   23.65 1028.48   26.16 1238.17   26.18 1303.08   28.65
#Mann= 3 , 0 , 0
       0      .3       0  569.16     .25       0 1028.48      .3       0
Bank Sta=569.16,1028.48
XS Rating Curve= 0 ,0
Exp/Cntr=0.3,0.1

Type RM Length L Ch R = 1 ,35617.03,2184.5,2339.95,2373.94
XS GIS Cut Line= 2
2133041.37347743468594.8043433282134044.90036113468852.559271637
#Sta/Elev= 30
       0   27.06   19.92   25.25   64.76   24.17   99.63   25.51  139.48   24.68
     150  25.586     300 25.5235  368.61   24.66  383.56   25.17  433.37    23.8
   478.2   24.93     490   24.57     508   21.26     520   21.14     566   21.67
     572   24.54     578   25.13     619   21.18     642   21.78     655   24.44
     677   25.09     686   24.31     708   20.12     760   20.11     856   22.34
     906   21.74     927    24.4  936.48   25.57  1011.2   25.77  1036.1   26.94
#Mann= 3 , 0 , 0
       0      .3       0     677     .25       0     927      .3       0
Bank Sta=677,927
XS Rating Curve= 0 ,0
Exp/Cntr=0.3,0.1

Type RM Length L Ch R = 1 ,33277.08,3132.39,3070.91,2988.05
XS GIS Cut Line= 3
2133755.80380708466345.9318725912134980.54184318466954.781376675
2135098.98357765467013.661879417
#Sta/Elev= 30
       0    26.2   79.87   23.85  189.69   23.23  209.65   24.07  244.59   22.96
  369.39   23.85  409.32   23.17  434.28   24.67  449.25   23.36  459.24   24.16
  494.18   23.93  509.15   25.04   539.1   23.28  623.96   23.53  653.91   22.68
  673.88   23.73  763.73   23.41   783.7    24.4  793.68   23.08  803.67   24.17
  838.61    23.4  868.56   24.31  918.48   23.48 1158.08    23.3 1232.95   24.15
  1262.9   23.32 1282.87   24.75  1322.8   23.81    1400  25.617    1500 29.7585
#Mann= 3 , 0 , 0
       0      .3       0  509.15     .25       0 1282.87      .3       0
Bank Sta=509.15,1282.87
XS Rating Curve= 0 ,0
Exp/Cntr=0.3,0.1

Type RM Length L Ch R = 1 ,30206.17,979.2,890.68,832.62
XS GIS Cut Line= 4
2135210.10629307463879.169575869 2135406.3848235463917.571899921
2136377.72868133464107.6174515782136720.47024158464174.675587962
#Sta/Elev= 30
    -200 24.8456       0    22.8   64.98    23.6   94.98   22.24     140 23.2287
  169.96   22.04  204.95   23.91     240 22.3052     260 23.4431  339.92   22.49
  359.91    24.6   394.9   23.35     431   19.94     458    19.3     490   20.02
     523   23.83     564   22.98     623    23.9     666   19.37     703   18.83
     729   18.96     754   24.71     811   22.78     831   19.58     840   16.29
     863   13.73     874    16.7  909.78   22.97    1289 23.6145    1339 24.9009
#Mann= 3 , 0 , 0
    -200      .3       0   394.9     .25       0  909.78      .3       0
Bank Sta=394.9,909.78
XS Rating Curve= 0 ,0
Exp/Cntr=0.3,0.1

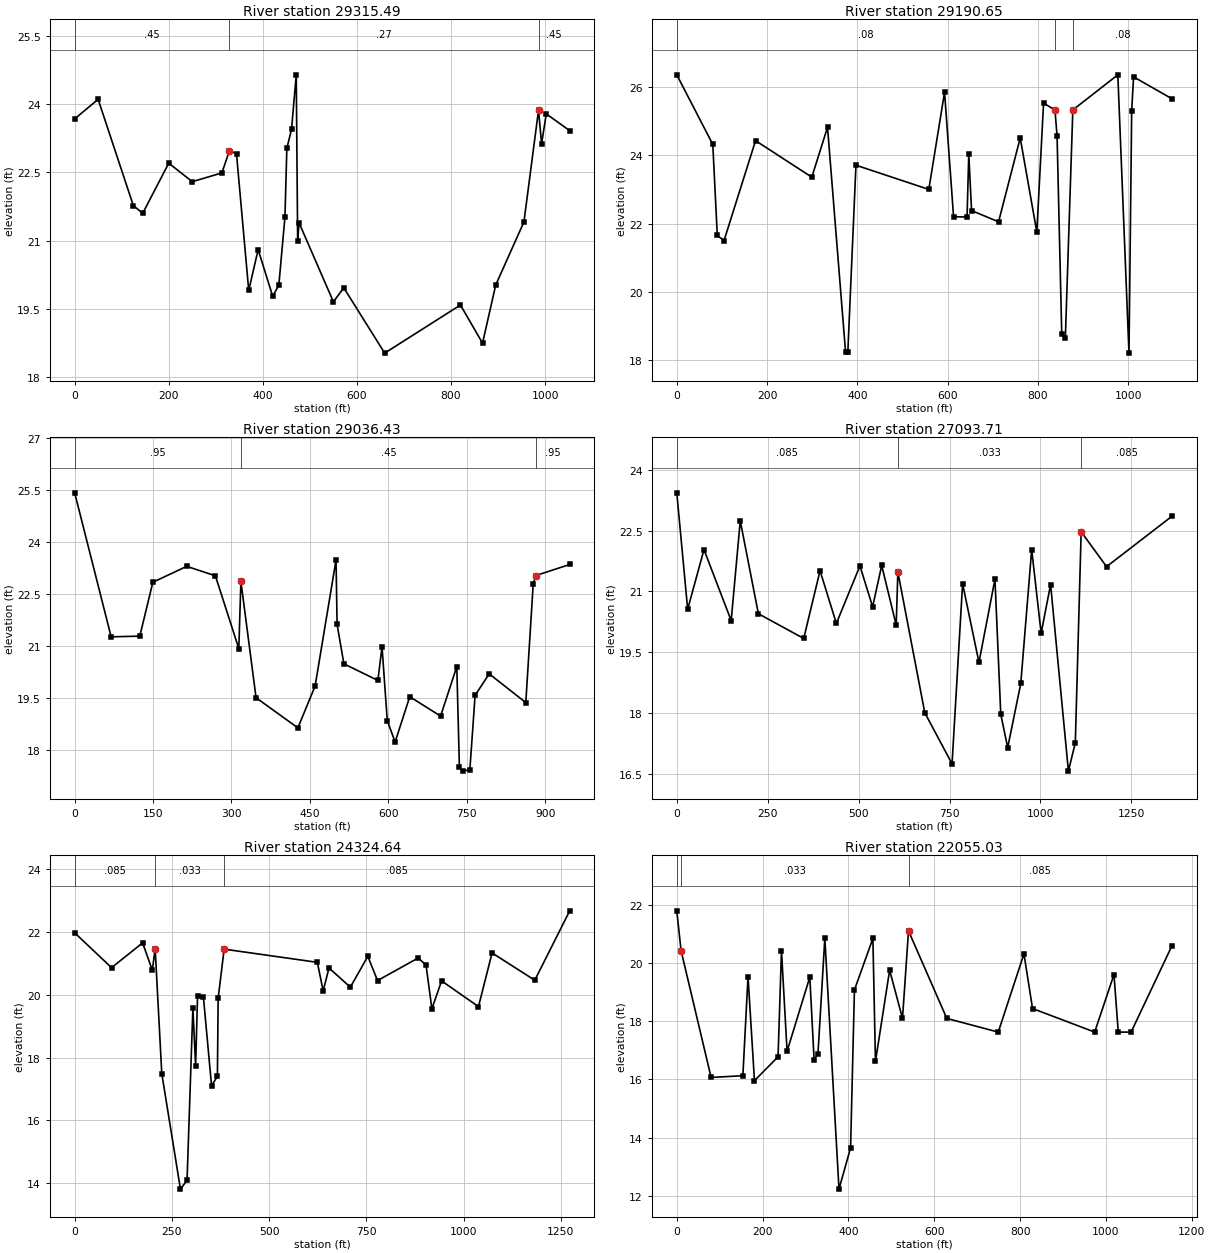
Type RM Length L Ch R = 1 ,29315.49,103.77,124.84,103.75
BEGIN DESCRIPTION:
Upstream of Tram
END DESCRIPTION:
XS GIS Cut Line= 2
2135494.36889949463101.0797664972136546.65813351463108.118466333
#Sta/Elev= 30
       0   23.68   49.87   24.11  124.68   21.77  144.63    21.6     200 22.7041
     250 22.2962     313   22.49     329   22.98     344   22.91     370    19.9
     390    20.8     421   19.77     434   20.02     447   21.52     451   23.03
     461   23.45     471   24.65     474   20.99     477   21.39     550   19.65
     572   19.96     659   18.52     820   19.58     867   18.74     895   20.02
     955   21.41     986   23.87  992.47   23.13 1002.44   23.79 1052.31   23.42
#Mann= 3 , 0 , 0
       0     .45       0     329     .27       0     986     .45       0
Bank Sta=329,986
XS Rating Curve= 0 ,0
Exp/Cntr=0.3,0.1

Type RM Length L Ch R = 1 ,29190.65,134.59,154.22,152.44
BEGIN DESCRIPTION:
Tram
END DESCRIPTION:
XS GIS Cut Line= 2
2135474.43718085463000.6613321752136571.38150924463004.093740001
#Sta/Elev= 30
       0   26.36   79.78   24.32   89.75   21.65  104.71    21.5  174.51   24.43
  299.17   23.36     334   24.82     374   18.23     379   18.23     397   23.71
  558.45      23  593.35   25.85  613.29    22.2  643.21   22.19     647   24.04
  653.18   22.38  713.02   22.05     761   24.51  797.78   21.75  812.74   25.53
     838   25.33  842.66   24.56     853   18.76     861   18.64  877.56   25.33
  977.28   26.36    1002    18.2    1008   25.31 1012.18    26.3 1096.95   25.66
#Mann= 3 , 0 , 0
       0     .08       0     838     .04       0  877.56     .08       0
Bank Sta=838,877.56
XS Rating Curve= 0 ,0
Exp/Cntr=0.3,0.1

Type RM Length L Ch R = 1 ,29036.43,2036.18,1942.72,1815.57
BEGIN DESCRIPTION:
Downstream of Tram
END DESCRIPTION:
XS GIS Cut Line= 2
2135529.56239867462847.6855882562136476.27080709462872.321365744
#Sta/Elev= 30
       0   25.42   69.78   21.26  124.61   21.28  149.53 22.8367  214.33 23.2962
  269.16 23.0233  314.01   20.92     318   22.86     347    19.5     427   18.63
     460   19.84     500   23.48     502   21.62     515   20.48     580      20
     588   20.97     598   18.84     613   18.22     641   19.53     700   18.97
     731    20.4     736   17.49     742   17.38     756   17.42     766   19.57
     793   20.19     863   19.36  877.25    22.8  882.23   23.03  947.03   23.35
#Mann= 3 , 0 , 0
       0     .95       0     318     .45       0  882.23     .95       0
Bank Sta=318,882.23
XS Rating Curve= 0 ,0
Exp/Cntr=0.3,0.1

Type RM Length L Ch R = 1 ,27093.71,2704.05,2769.07,2342.7
XS GIS Cut Line= 2
2135881.49870268461059.8495970072137225.89496401460845.168595925
#Sta/Elev= 30
       0   23.43   29.92   20.56    74.8   22.03  149.61   20.28  174.54   22.74
  224.41   20.45  349.08   19.84  393.97   21.51  438.85   20.21  503.68   21.63
  538.59   20.62  563.52   21.64  603.42   20.17     608   21.48     682   18.01
     757   16.75     786   21.19     831   19.25     875    21.3     891   17.97
     910   17.15     946   18.73     976   22.03    1002   19.97    1028   21.17
    1077   16.57    1096   17.27 1112.08   22.47  1181.9   21.61 1361.43   22.85
#Mann= 3 , 0 , 0
       0    .085       0     608    .033       0 1112.08    .085       0
Bank Sta=608,1112.08
XS Rating Curve= 0 ,0
Exp/Cntr=0.3,0.1

Type RM Length L Ch R = 1 ,24324.64,2255.47,2269.61,2144.53
XS GIS Cut Line= 2
2134382.25038883459229.7814067452135480.29149985 458585.73807542
#Sta/Elev= 30
       0   21.97   94.85   20.86  174.72   21.65  199.68   20.78     207   21.46
     224   17.49     272   13.81     289   14.09     304   19.58     311   17.73
     316   19.96     331   19.93     352    17.1     367    17.4     369   19.89
  384.39   21.45  624.01   21.03  638.99   20.12  653.96   20.85  708.88   20.24
  753.81   21.22  778.77   20.45   883.6   21.17  903.57   20.94  918.55   19.55
  943.51   20.44 1038.36   19.62  1073.3   21.33 1183.13   20.46 1272.98   22.67
#Mann= 3 , 0 , 0
       0    .085       0     207    .033       0  384.39    .085       0
Bank Sta=207,384.39
XS Rating Curve= 0 ,0
Exp/Cntr=0.3,0.1

Type RM Length L Ch R = 1 ,22055.03,318.72,329.16,338.13
XS GIS Cut Line= 2
2134093.66271141   457111.1252112134989.56413484456384.300549164
#Sta/Elev= 30
       0    21.8    9.99   20.43      80   16.07     154   16.13     166   19.54
     181   15.96     236   16.78     244   20.43     257   16.97     310   19.52
     320   16.68     329   16.88     345   20.86     378   12.23     405   13.65
     414   19.08     457   20.85     463   16.62     496   19.76     526    18.1
     540   21.11  629.26    18.1  749.12   17.63  809.05   20.32  829.03   18.44
  973.86   17.63 1018.81   19.61  1028.8   17.63 1058.76   17.63 1153.65   20.59
#Mann= 3 , 0 , 0
       0    .085       0    9.99    .033       0     540    .085       0
Bank Sta=9.99,540
XS Rating Curve= 0 ,0
Exp/Cntr=0.3,0.1

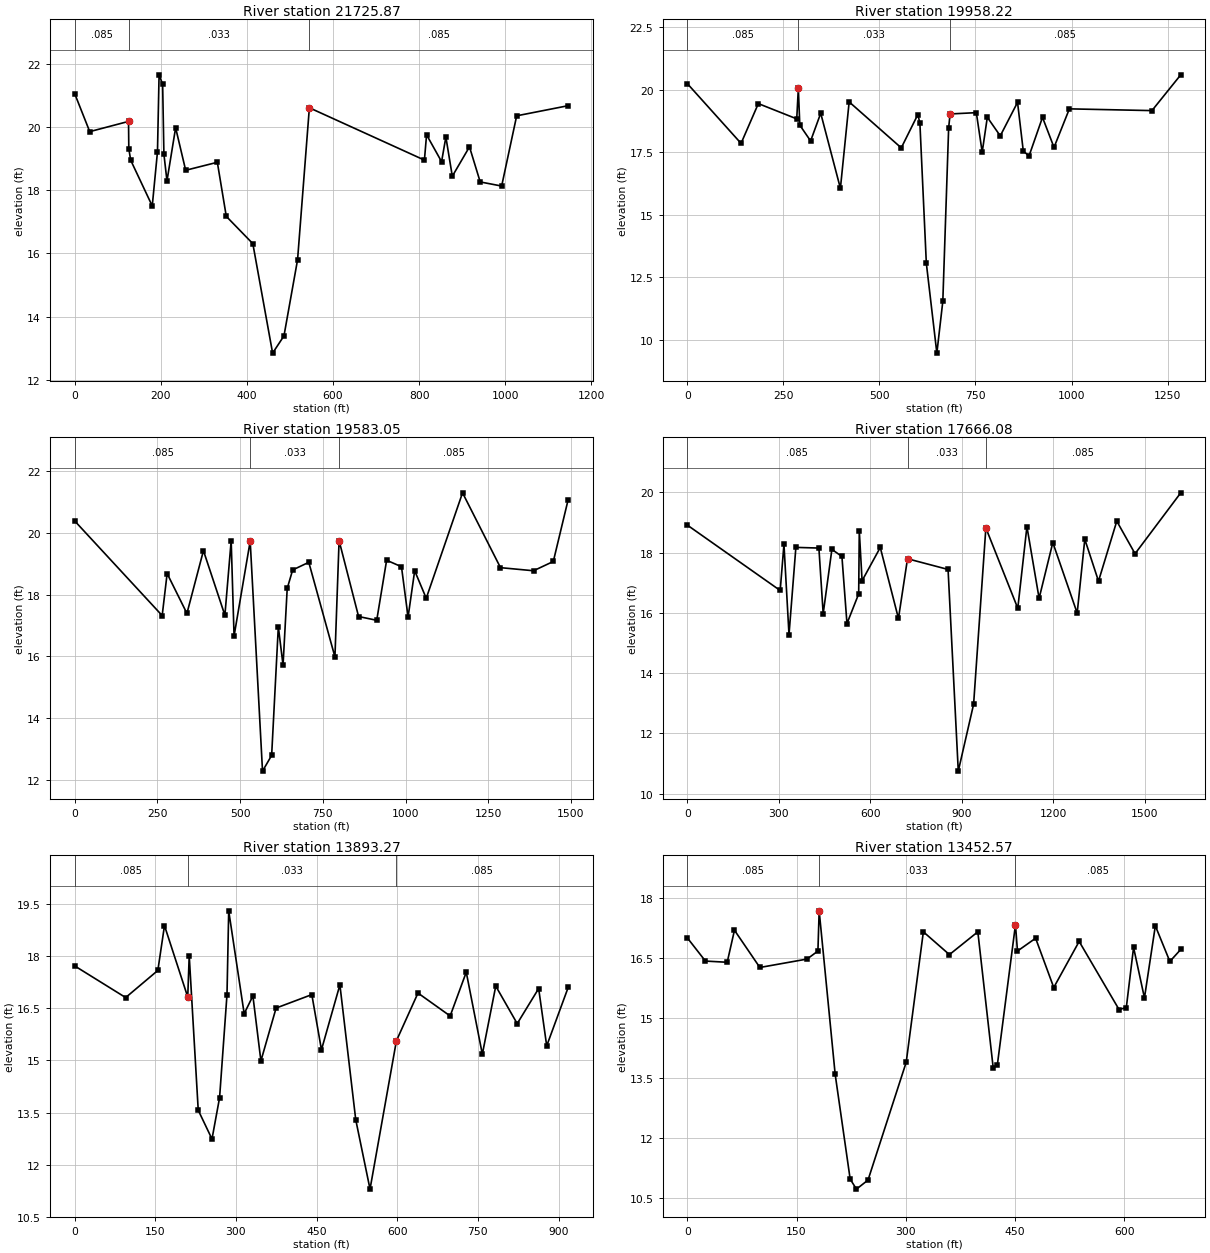
Type RM Length L Ch R = 1 ,21725.87,1659.14,1767.66,1804.93
XS GIS Cut Line= 2
2133864.90431067456857.7313608382134769.38019201456153.858752832
#Sta/Elev= 30
       0   21.05   34.88   19.85     125 20.1735125.6404 19.3092130.0349 18.9465
180.0837 17.5003192.2236  19.214195.9398 21.6457204.2141 21.3475207.1566 19.1399
214.2751 18.2919234.3668 19.9729 257.698 18.6284331.2491 18.8811352.0523 17.1718
 413.703 16.3088459.6342 12.8488485.9987 13.3937517.5822 15.7991     545  20.604
  812.23   18.95  817.21   19.75  852.09    18.9  862.06   19.68     877   18.44
  916.87   19.37  941.78   18.26  991.61   18.13 1026.49   20.35 1146.08   20.67
#Mann= 3 , 0 , 0
       0    .085       0     125    .033       0     545    .085       0
Bank Sta=125,545
XS Rating Curve= 0 ,0
Exp/Cntr=0.3,0.1

Type RM Length L Ch R = 1 ,19958.22,226.58,375.17,421.64
XS GIS Cut Line= 2
2132883.00207502455312.7311699992134002.15928552454682.765566424
#Sta/Elev= 30
       0   20.25  139.92   17.86   184.9   19.45  284.84   18.84     289  20.058
 292.814  18.589 320.977  17.957 347.242  19.065 398.484  16.063 421.261  19.518
 556.895  17.681 599.965   19.01 605.353  18.676 622.123   13.07 649.518   9.477
 665.024  11.546  680.25  18.488 683.989  19.036  752.25  19.088 767.536  17.509
 780.853  18.903  814.54   18.16  859.52    19.5  874.51   17.55   889.5   17.36
  924.48    18.9  954.46    17.7  994.44   19.24 1209.32   19.17 1284.28    20.6
#Mann= 3 , 0 , 0
       0    .085       0     289    .033       0 683.989    .085       0
Bank Sta=289,683.989
XS Rating Curve= 0 ,0
Exp/Cntr=0.3,0.1

Type RM Length L Ch R = 1 ,19583.05,1560.82,1916.97,2072.7
XS GIS Cut Line= 2
2132569.77894819454950.2371443362133977.52383608454457.526187494
#Sta/Elev= 30
       0   20.38  264.38   17.32  279.34   18.68   339.2   17.39  389.08   19.42
  453.93   17.33 472.918  19.744 481.645  16.659  530.39  19.728 567.657   12.29
 595.238    12.8 615.431  16.961 629.699  15.716 642.282  18.197 658.736  18.796
 707.526  19.043 786.548  15.983 799.082  19.744  857.98   17.29  912.85  17.168
  942.77   19.11  987.67    18.9 1007.62   17.27 1027.58   18.77 1062.49   17.88
 1172.23   21.29 1286.96   18.87 1386.73   18.77 1446.59   19.07 1491.48   21.07
#Mann= 3 , 0 , 0
       0    .085       0  530.39    .033       0 799.082    .085       0
Bank Sta=530.39,799.082
XS Rating Curve= 0 ,0
Exp/Cntr=0.3,0.1

Type RM Length L Ch R = 1 ,17666.08,3631.22,3772.81,3705.93
XS GIS Cut Line= 2
2132432.52364525 452764.71297209 2134044.3914845452905.487624913
#Sta/Elev= 30
       0   18.91  304.62   16.74 316.948  18.273 333.478  15.275 356.031   18.17
 431.494  18.148  445.56   15.97 474.116  18.104 507.016  17.868 523.587  15.643
  561.99  16.628 563.928  18.726 573.122  17.064 632.769  18.167 692.375  15.813
  722.08  17.793 855.065  17.438 888.548  10.748 938.775  12.966     979  18.815
 1083.66   16.15 1113.63   18.86 1153.58   16.48 1198.52   18.33 1278.42   15.99
 1303.39   18.44 1348.34   17.05 1408.26   19.04 1468.19   17.96    1618   19.98
#Mann= 3 , 0 , 0
       0    .085       0  722.08    .033       0     979    .085       0
Bank Sta=722.08,979
XS Rating Curve= 0 ,0
Exp/Cntr=0.3,0.1

Type RM Length L Ch R = 1 ,13893.27,473.71,440.69,363.34
XS GIS Cut Line= 2
2134347.89251792449287.9597550032133438.83000363449160.521003741
#Sta/Elev= 30
       0   17.72   94.79   16.81  154.65   17.59     167   18.88 210.265  16.825
 213.005  18.016 229.776  13.569 255.363   12.74 269.488  13.929 283.289  16.896
 286.471  19.305 315.235  16.346 331.488  16.857 346.371  14.987 374.629  16.508
 441.081  16.895 459.025  15.308 493.318  17.176 522.773  13.297  549.36  11.299
  598.46  15.567  638.57   16.94  698.44   16.28  728.37   17.54   758.3   15.18
  783.25   17.14  823.16   16.06  863.07   17.07  878.03   15.42  917.95    17.1
#Mann= 3 , 0 , 0
       0    .085       0 210.265    .033       0  598.46    .085       0
Bank Sta=210.265,598.46
XS Rating Curve= 0 ,0
Exp/Cntr=0.3,0.1

Type RM Length L Ch R = 1 ,13452.57,823.98,989.33,1255.54
XS GIS Cut Line= 2
2134235.04530266 448827.890465172133557.96201116448810.529279411
#Sta/Elev= 30
       0      17    24.9   16.42   54.78   16.39   64.74   17.19    99.6   16.26
  164.35   16.47  179.29   16.67     181  17.674 202.985  13.592 223.564  10.978
 232.185  10.728  248.06  10.954 300.476  13.895 324.021   17.15 359.794  16.581
 398.786   17.15 419.861   13.76 425.545  13.824  450.45  17.327   453.2   16.67
   478.1   16.99     503   15.76  537.86   16.91  592.64   15.21   602.6   15.26
  612.56   16.76   627.5    15.5  642.44    17.3  662.36   16.41  677.31   16.71
#Mann= 3 , 0 , 0
       0    .085       0     181    .033       0  450.45    .085       0
Bank Sta=181,450.45
XS Rating Curve= 0 ,0
Exp/Cntr=0.3,0.1

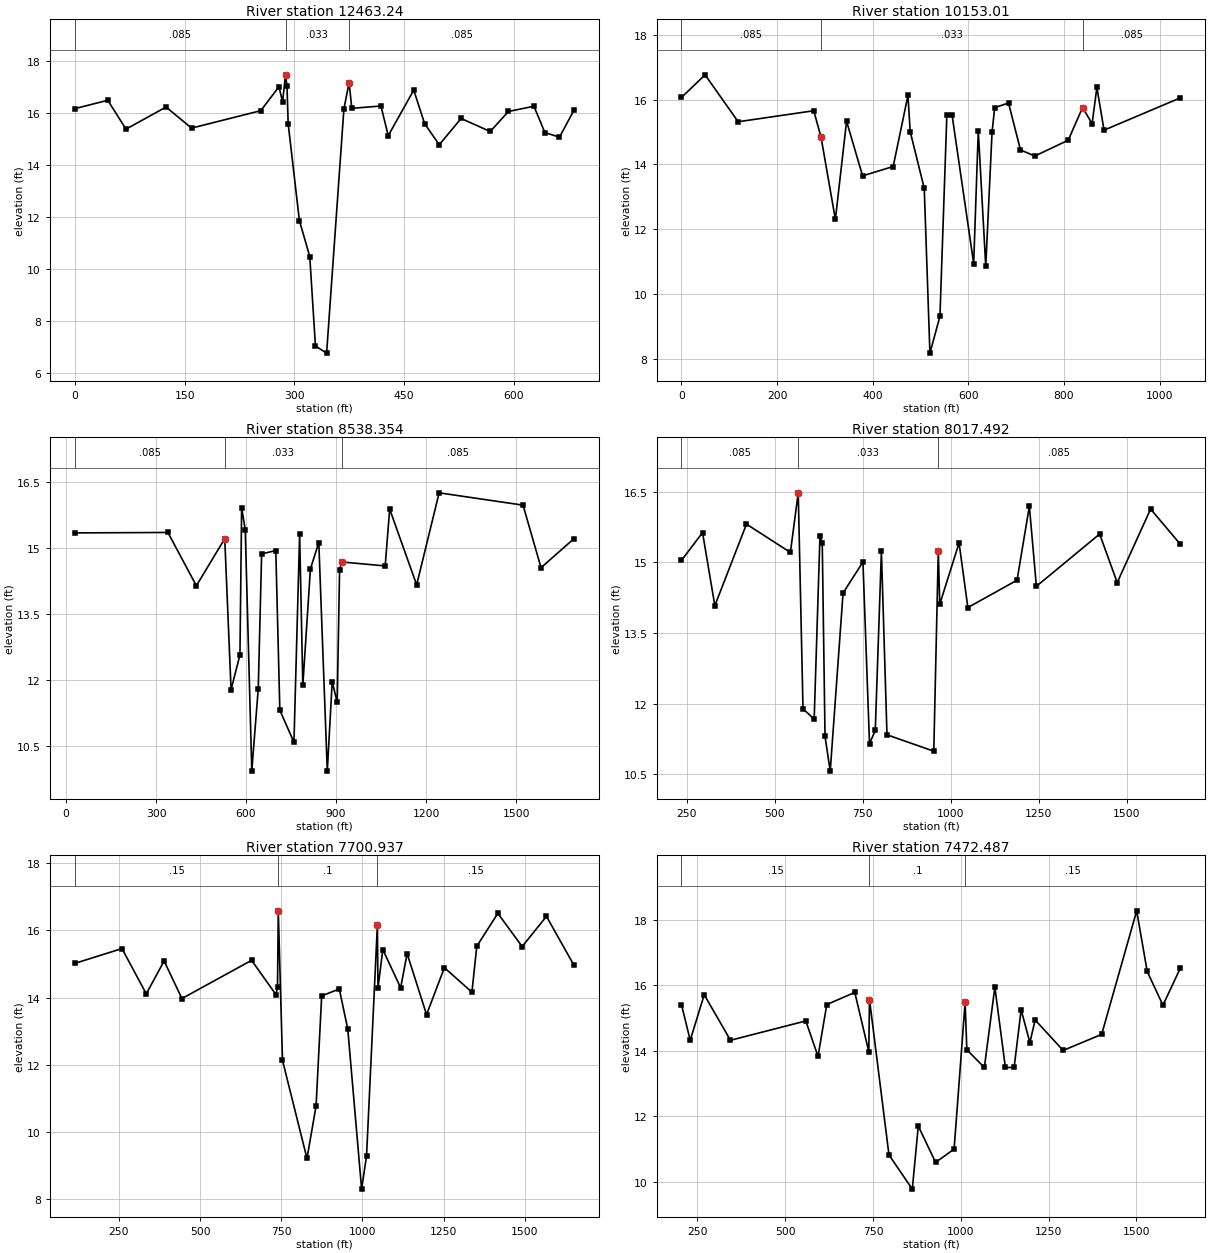
Type RM Length L Ch R = 1 ,12463.24,2195.56,2310.23,2373.73
XS GIS Cut Line= 2
2134816.64256468448246.293203175 2134304.4897176447794.904342175
#Sta/Elev= 30
       0   16.16   44.85   16.48   69.76   15.37  124.58   16.22  159.46   15.41
  254.14   16.08  279.05      17  284.03   16.42     288  17.458 290.047   17.01
 291.628  15.584  306.99  11.857  321.18  10.475  328.95   7.035 344.231   6.762
 367.878  16.141  375.01  17.162  378.71   16.17  418.58   16.26  428.54   15.12
  463.43   16.87  478.37   15.58  498.31   14.77  528.21   15.78  568.07   15.28
  592.98   16.05  627.87   16.25  642.82   15.24  662.75   15.06  682.68    16.1
#Mann= 3 , 0 , 0
       0    .085       0     288    .033       0  375.01    .085       0
Bank Sta=288,375.01
XS Rating Curve= 0 ,0
Exp/Cntr=0.3,0.1

Type RM Length L Ch R = 1 ,10153.01,1985.28,1614.66,672.62
XS GIS Cut Line= 4
2136283.65636292446614.3486324252136066.37792608446419.933010757
  2135860.763836446121.2738311742135632.78974643445805.319218313
#Sta/Elev= 30
       0   16.07   49.42   16.77   118.6   15.32  276.73   15.66     292  14.841
 321.947  12.302 345.378  15.336 378.836  13.648 442.872  13.937 473.763  16.133
 478.431  15.017 507.849  13.264 519.711    8.17 540.681    9.31 555.123  15.531
 566.148  15.515 611.245  10.938 620.849   15.04 636.492  10.848 649.643  14.992
 655.174  15.754  684.12    15.9   709.1   14.45  739.07   14.26     809   14.75
  838.97   15.76  858.95   15.26  868.94   16.38  883.93   15.06 1043.77   16.06
#Mann= 3 , 0 , 0
       0    .085       0     292    .033       0  838.97    .085       0
Bank Sta=292,838.97
XS Rating Curve= 0 ,0
Exp/Cntr=0.3,0.1

Type RM Length L Ch R = 1 ,8538.354,560.49,520.86,491.84
XS GIS Cut Line= 2
2137185.43736742444639.4062141032135684.69791517445355.668078914
#Sta/Elev= 30
   29.96   15.34  339.57   15.35  434.45   14.14     529  15.209550.0571 11.7803
 579.659 12.5722585.3088 15.9098 597.337 15.4113 619.123  9.9395640.6998 11.8068
651.9254 14.8641 699.132 14.9395 712.614  11.313759.6281 10.5878 778.574   15.31
789.1758 11.8775814.4901 14.5223842.4488 15.1221 870.731  9.9309887.1095 11.9644
903.7103 11.4912911.7265 14.5068  918.84   14.68 1063.66   14.59 1078.64   15.88
 1168.53   14.16 1243.43   16.25 1523.08   15.97    1583   14.55 1692.87   15.21
#Mann= 3 , 0 , 0
   29.96    .085       0     529    .033       0  918.84    .085       0
Bank Sta=529,918.84
XS Rating Curve= 0 ,0
Exp/Cntr=0.3,0.1

Type RM Length L Ch R = 1 ,8017.492,362.91,316.55,264.33
XS GIS Cut Line= 2
2136844.16630631444179.3621314832135615.25350025444886.918032169
#Sta/Elev= 30
  234.68   15.04  294.59   15.63  329.55   14.08  419.42   15.81  544.25   15.21
566.5404 16.4742 580.122 11.8884 611.842  11.674628.3062 15.5615634.7617 15.4158
642.6641 11.3043657.4349 10.5684693.9042 14.3472750.4171 15.0074769.0693 11.1516
  785.45 11.4311802.8633   15.23818.7316 11.3395951.7188  10.991964.5404 15.2399
  968.67   14.11 1023.59   15.41 1048.56   14.04 1188.37   14.62 1223.32   16.19
 1243.29   14.49 1423.05    15.6 1472.98   14.57 1567.85   16.13 1652.73   15.38
#Mann= 3 , 0 , 0
  234.68    .085       0566.5404    .033       0964.5404    .085       0
Bank Sta=566.5404,964.5404
XS Rating Curve= 0 ,0
Exp/Cntr=0.3,0.1

Type RM Length L Ch R = 1 ,7700.937,230.14,228.45,232.66
XS GIS Cut Line= 2
2136788.51853122443772.1093956872135528.44789958444652.543172836
#Sta/Elev= 30
  114.79   15.02  259.52   15.46  334.39   14.11  389.29   15.09  444.19   13.97
  658.79   15.11  733.66   14.09  738.65    14.3     741 16.5852753.9977 12.1254
829.4193  9.2027857.4589  10.768874.7121 14.0504 928.993 14.2547955.1064  13.058
997.7247  8.28811012.937  9.2792  1046.3 16.1624 1048.08   14.28 1063.06   15.43
 1117.96   14.29 1137.92   15.31 1197.81   13.49 1252.71   14.89 1337.56   14.16
 1352.53   15.53 1417.41   16.51 1492.27   15.52 1567.14   16.42 1651.98   14.96
#Mann= 3 , 0 , 0
  114.79     .15       0     741      .1       0  1046.3     .15       0
Bank Sta=741,1046.3
XS Rating Curve= 0 ,0
Exp/Cntr=0.3,0.1

Type RM Length L Ch R = 1 ,7472.487,2136.86,2484.53,2720.14
XS GIS Cut Line= 2
2136585.36916173443633.2989235952135424.28144127444452.890356913
#Sta/Elev= 30
  204.46   15.41  229.39   14.32  269.28   15.71  344.08   14.32  558.51   14.91
  593.42   13.83  618.36   15.41  698.14   15.78  738.04   13.97     740  15.562
 795.443  10.823 861.929   9.778 878.944  11.702 928.287  10.595 980.965  10.998
 1012.33  15.473 1017.29   14.03 1067.16   13.49 1097.08   15.94    1127   13.49
 1151.93   13.49 1171.88   15.25 1196.82   14.25 1211.78   14.94 1291.56   14.01
 1401.27    14.5 1501.01   18.27 1530.93   16.42 1575.81   15.39 1625.68   16.53
#Mann= 3 , 0 , 0
  204.46     .15       0     740      .1       0 1012.33     .15       0
Bank Sta=740,1012.33
XS Rating Curve= 0 ,0
Exp/Cntr=0.3,0.1

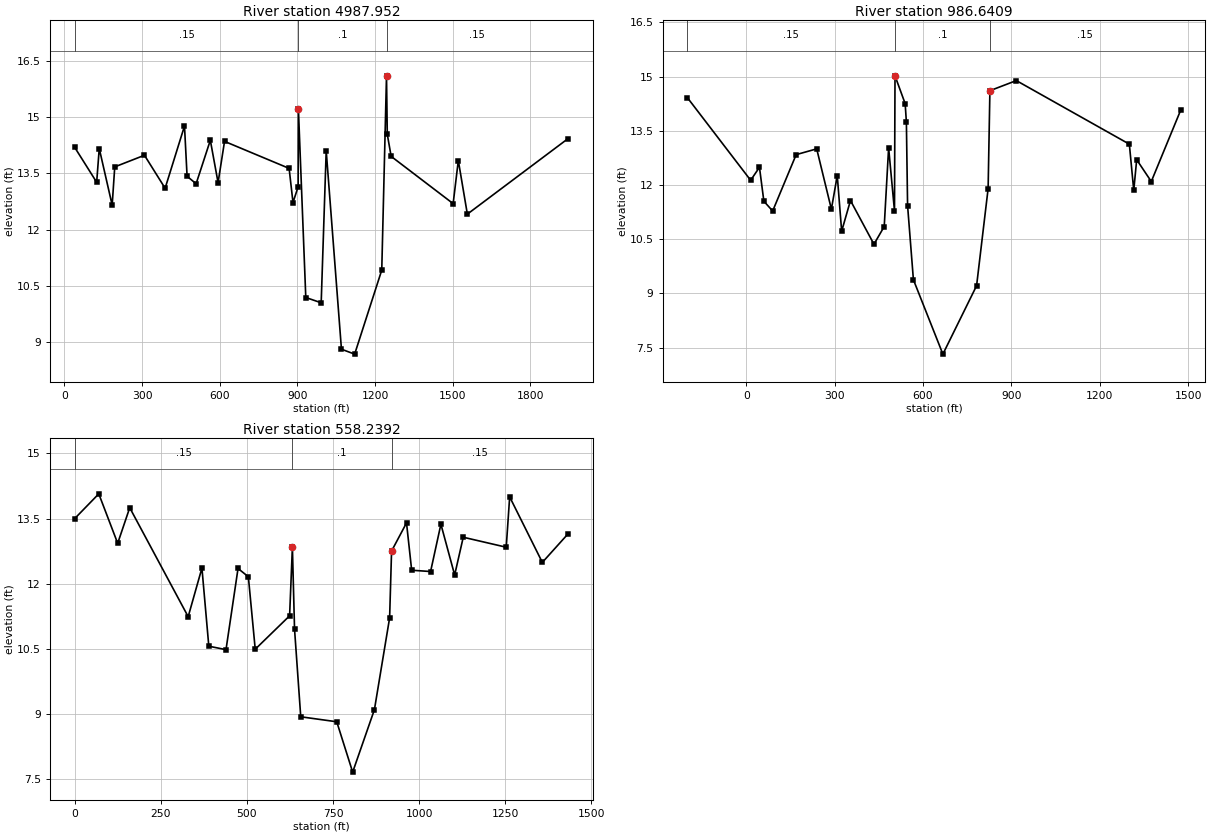
Type RM Length L Ch R = 1 ,4987.952,3878.48,4001.31,3628.66
XS GIS Cut Line= 3
2134578.66235527441732.7550410652136309.69797751441596.987604171
2136478.90830938 441583.71621174
#Sta/Elev= 30
   39.92   14.19  124.74   13.26  134.72   14.16  184.61   12.65  194.59   13.67
  309.35   13.98  389.18    13.1  464.03   14.76  474.01   13.42  508.93   13.22
  563.82   14.38  593.75   13.25   618.7   14.35  868.18   13.63  883.15   12.72
   903.1   13.14     904  15.226 932.596  10.187 992.072  10.0461011.463    14.1
1070.334   8.8081121.384   8.6771226.065  10.918 1244.42  16.098 1247.38   14.54
 1262.35   13.95 1501.85   12.69 1521.81   13.84 1556.73   12.41    1946 14.4253
#Mann= 3 , 0 , 0
   39.92     .15       0     904      .1       0 1244.42     .15       0
Bank Sta=904,1244.42
XS Rating Curve= 0 ,0
Exp/Cntr=0.3,0.1

Type RM Length L Ch R = 1 ,986.6409,410.35,428.4,445.04
BEGIN DESCRIPTION:
Goose Pasture
END DESCRIPTION:
XS GIS Cut Line= 4
2135180.62696732438353.2123859172135354.83702633438254.973618925
2136509.35079342437603.9319420012136639.63373926437530.464106489
#Sta/Elev= 30
    -200 14.4184   14.95   12.13   44.85   12.49   59.79   11.55   89.69   11.28
  169.42   12.84  239.17      13     289   11.33  308.93   12.26  323.88   10.72
  353.78   11.57   433.5   10.36  468.38   10.85  483.33   13.03  503.26   11.28
     505 15.0216539.4906 14.2504543.6213 13.7401547.6689 11.4284567.4429  9.3777
667.5197  7.3179781.9263  9.2112821.0906 11.8993  827.15   14.61  916.84   14.89
 1300.51   13.13 1315.46   11.85 1325.43    12.7    1375 12.0959    1475 14.0752
#Mann= 3 , 0 , 0
    -200     .15       0     505      .1       0  827.15     .15       0
Bank Sta=505,827.15
XS Rating Curve= 0 ,0
Exp/Cntr=0.3,0.1

Type RM Length L Ch R = 1 ,558.2392,0,558.24,0
XS GIS Cut Line= 2
2135077.05903858437890.3903585822136353.10077783437239.348681673
#Sta/Elev= 30
       0    13.5   69.88   14.07  124.78   12.93  159.72   13.75  329.43   11.24
  369.36   12.36  389.33   10.56  439.24   10.48  474.18   12.35  504.13   12.16
   524.1   10.49  623.92   11.26     632  12.842 638.216  10.955  656.25   8.934
 760.792   8.819 807.018   7.659  870.16   9.099 914.277  11.212  919.94  12.752
  963.34    13.4  978.31   12.31 1033.22   12.28 1063.17   13.37  1103.1    12.2
 1128.05   13.07 1252.84   12.84 1262.82      14 1357.66   12.49 1432.53   13.15
#Mann= 3 , 0 , 0
       0     .15       0     632      .1       0  919.94     .15       0
Bank Sta=632,919.94
XS Rating Curve= 0 ,0
Exp/Cntr=0.3,0.1

Chan Stop Cuts=-1
Use User Specified Reach Order=0
Composite Channel Slope=5